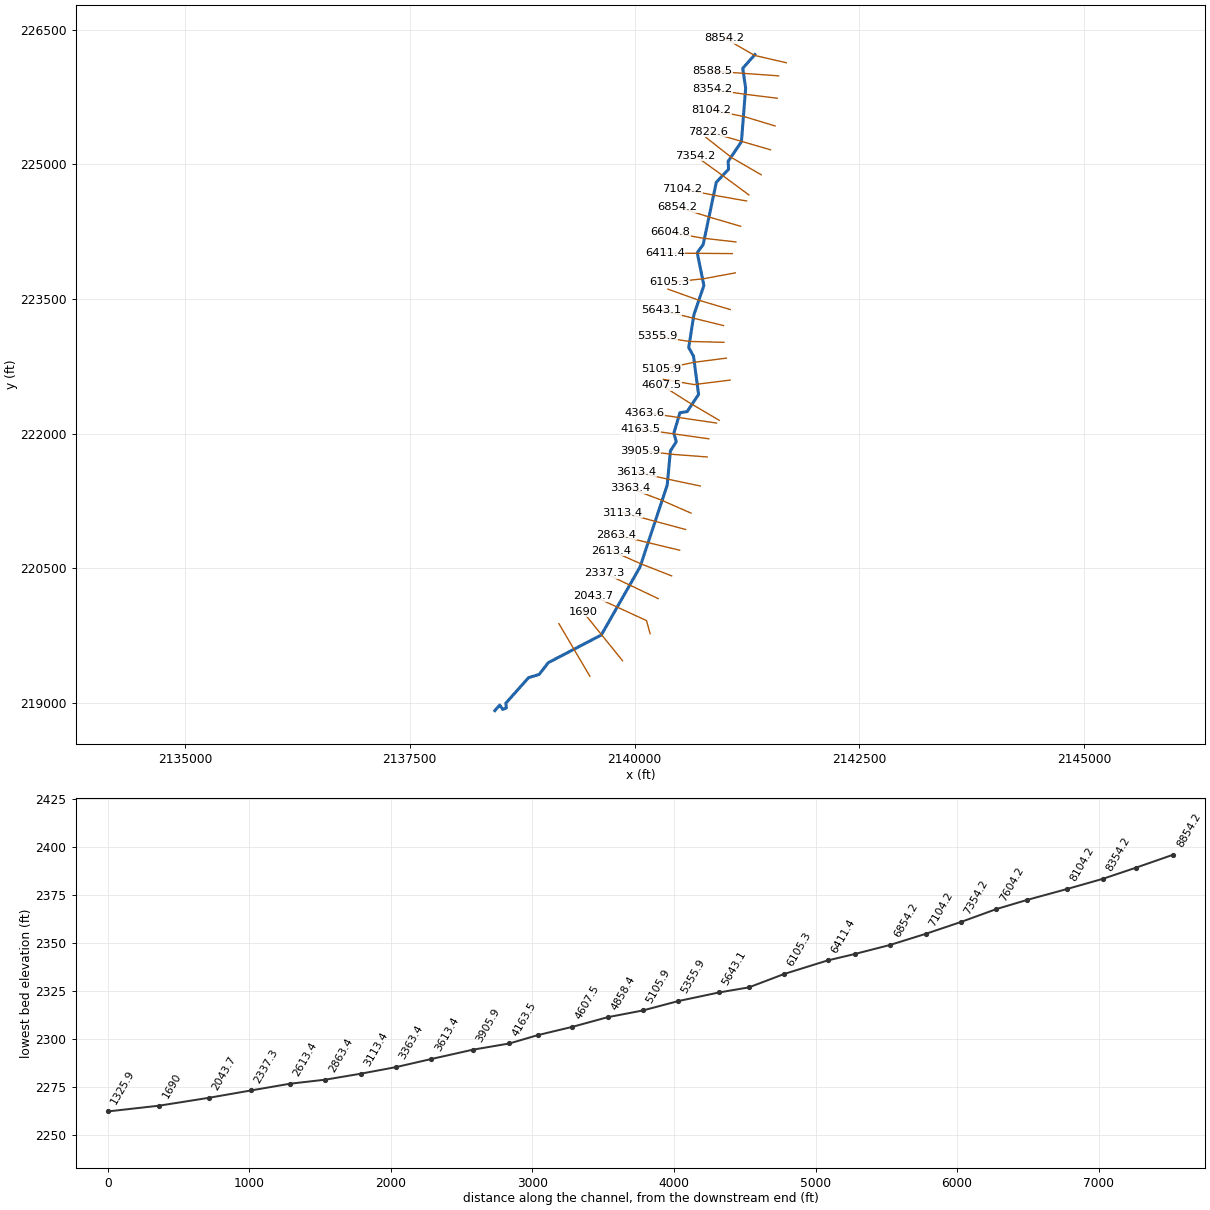
--- FORESTRN.prj (project) ---

Proj Title=FORESTRN
Current Plan=p01
Default Exp/Contr=0,0
English Units
Geom File=g01
Flow File=f01
Plan File=p01
BEGIN DESCRIPTION:
END DESCRIPTION:
DSS Export Rating Curves= 0
DSS Export Rating Curve Sorted= 0
DSS Export Volume Flow Curves= 0
DXF OffsetX= 0
DXF OffsetY= 0
DXF ScaleX= 0
DXF ScaleY= 0

--- FORESTRN.p01 (plan) ---

Plan Title=Floodplain
Program Version=4.00
Geom File=g01
Flow File=f01
K Sum by GR=0
Std Step Tol=0.01
Critical Tol=0.01
Num of Std Step Trials=20
Max Error Tol=0.3
Flow Tol Ratio=0.001
Split Flow NTrial=30
Split Flow Tol=0.02
Split Flow Ratio=0.02
Log Output Level=0
Friction Slope Method=1
Unsteady Friction Slope Method=2
Unsteady Bridges Friction Slope Method=1
Global Log Level=0
CheckData=False
Run HTab=0
Run UNet=0
Run PostProcess=0
UNET Theta=0
UNET Theta Warmup=0
UNET ZTol=0
UNET ZSATol=0
UNET MxIter=0
UNET MaxInSteps=0
UNET DtIC=0
UNET DtMin=0
UNET MaxCRTS=0
UNET WFStab=0
UNET SFStab=0
UNET WFX=0
UNET SFX=0
UNET DSS MLevel=0
UNET DZMax Abort=0
UNET Convert EG Bridges=0
UNET Use Existing IB Tables=0
UNET Froude Limit=0
UNET Froude Power=0
Write IC File=0
Echo Input=False
Echo Output=False
Write Detailed=0

--- FORESTRN.f01 (steady flow) ---

Flow Title=2010 USGS WV Regression Equation
Program Version=4.10
Number of Profiles= 1
Profile Names=P100yr
River Rch & RM=FORESTRN,Main            ,8854.2
579.3604
River Rch & RM=FORESTRN,Main            ,5855.3
622.6653
River Rch & RM=FORESTRN,Main            ,2043.7
682.2436
River Rch & RM=FORESTRN,Main            ,1690
774.9393
River Rch & RM=FORESTRN,Main            ,458.3
782.7752
River Rch & RM=FORESTRN,Main            ,71.2
785.8507
Boundary for River Rch & Prof#=FORESTRN,Main            , 1
Up Type= 0
Dn Type= 3
Dn Slope=0.00503
DSS Import GetInterval= 0
DSS Import GetPeak= 0
DSS Import FillOption= 0

--- FORESTRN.g01 (geometry) ---

Geom Title=LiDAR
Program Version=4.10

River Reach=FORESTRN        ,Main
Reach XY= 30
     2141337.358      226223.775     2141202.809       226070.13
     2141234.927      225850.512     2141188.052      225252.421
     2141040.483      225034.539     2141044.823      224945.998
     2140908.538      224801.032     2140762.705      224107.456
     2140696.733      224017.178     2140770.518      223650.859
     2140659.407       223324.47     2140602.115      222959.886
     2140655.066      222863.532      2140711.49      222436.449
     2140583.886      222245.477     2140504.025      222233.324
     2140436.316      222004.157     2140464.094      221910.407
     2140398.047      221806.661     2140362.532      221425.164
     2140060.448      220514.574     2139630.235      219756.776
     2139040.374      219448.168     2138938.812      219317.091
     2138820.756      219280.633     2138567.979      218996.605
     2138574.923      218943.828     2138533.256      218927.161
     2138499.923      218975.772     2138446.052      218913.599

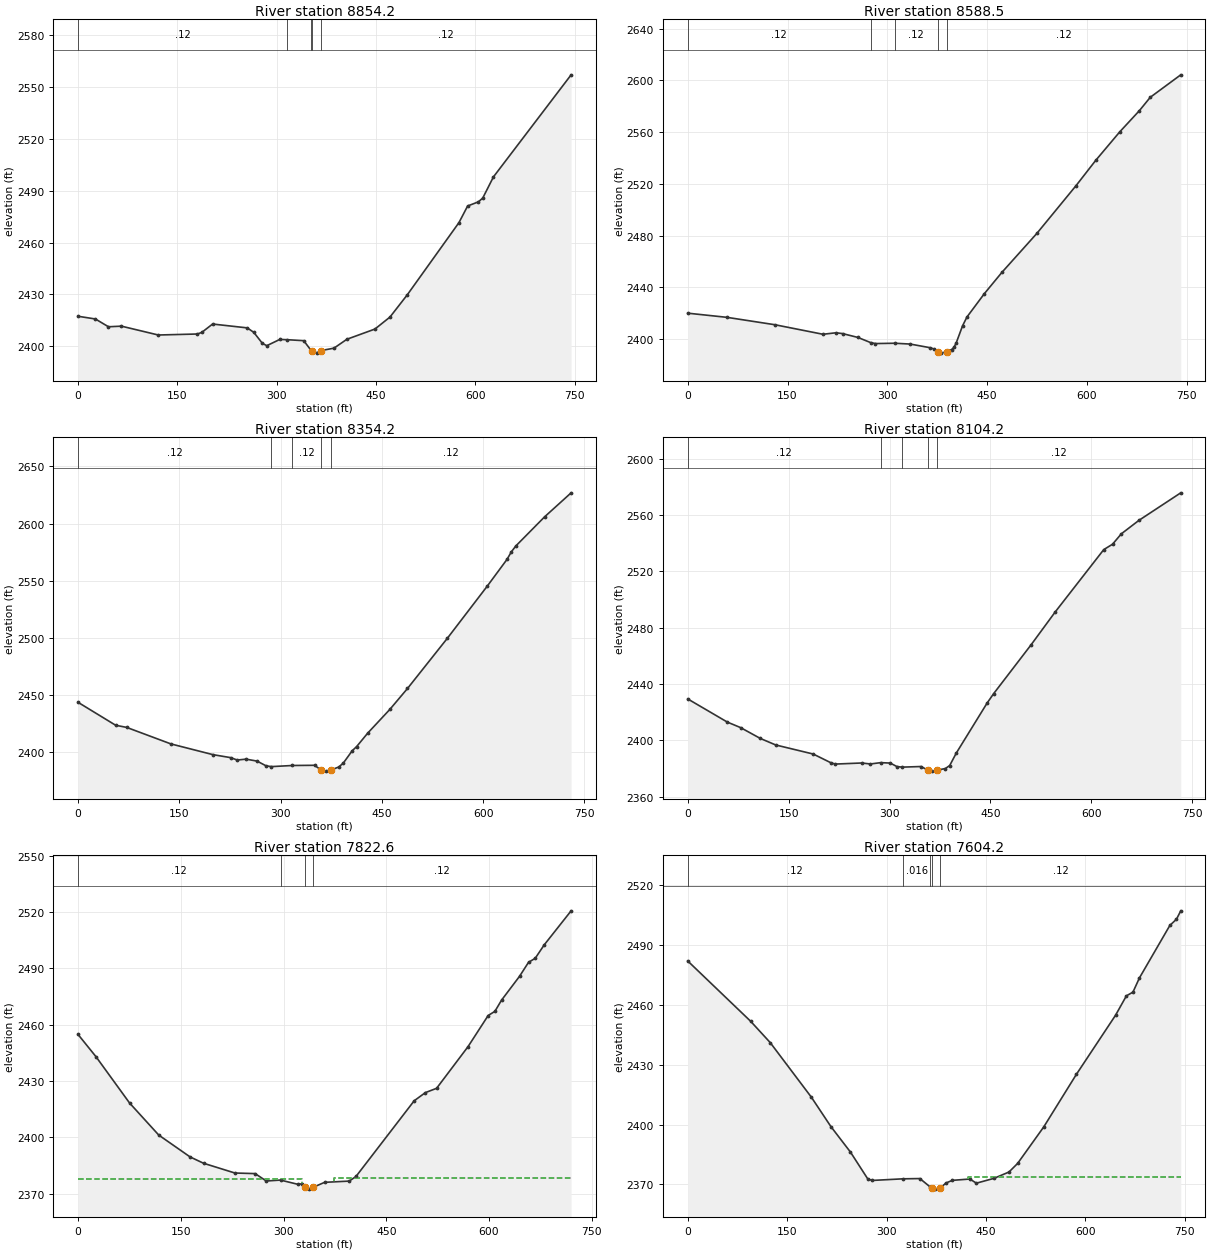
Type RM Length L Ch R = 1 ,8854.2  ,261.3,265.8,275.3
XS GIS Cut Line= 3
      2141686.31      226132.984     2141335.109      226214.031
     2141002.383      226406.184
#Sta/Elev= 30
       0 2417.31    26.2 2415.74    45.9 2411.24    65.5 2411.59   121.2 2406.47
   180.2 2407.05   186.8 2407.96   203.2 2412.82   255.6 2410.59   265.4    2408
   278.5 2401.59   285.1  2400.3   304.7 2403.91  316.152403.742   340.8 2403.19
  352.112397.471   352.9 2397.22   360.4 2395.98   366.9 2397.45   386.5 2398.86
     406    2404   448.4 2409.92   471.1 2416.86   497.2 2429.71   575.3 2471.53
   588.4 2481.15   604.6 2483.54   611.2 2485.72   627.4 2498.01   744.7 2557.07
#Mann= 5 ,-1 , 0
       0     .12       0  316.15    .016       0  352.11     .12       0
   352.9    .045       0   366.9     .12       0
Bank Sta=352.9,366.9
XS Rating Curve= 0 ,0
Exp/Cntr=0.3,0.1

Type RM Length L Ch R = 1 ,8588.5  ,235,234.2,232.2
XS GIS Cut Line= 2
     2141601.653      225986.569     2140862.721      226039.738
#Sta/Elev= 30
       0 2420.04      59 2416.82   131.1  2411.1   203.2 2403.74   222.9 2404.89
   232.7 2404.26   255.7 2401.29  274.78 2397.32   281.9 2396.55  311.312396.802
   334.4 2396.16   363.9 2393.38   370.4  2392.3  375.76 2390.25   380.3 2389.16
   389.1 2390.28   396.6 2391.94   399.9 2393.58   403.2 2396.75     413 2410.33
   419.6 2417.11   445.8 2435.19     472 2451.53   524.5 2481.64   583.5 2518.63
     613 2538.12   649.1 2560.16   678.6 2576.55     695  2586.9   740.8 2604.26
#Mann= 5 ,-1 , 0
       0     .12       0  274.78    .016       0  311.31     .12       0
  375.76    .045       0   389.1     .12       0
Bank Sta=375.76,389.1
XS Rating Curve= 0 ,0
Exp/Cntr=0.3,0.1

Type RM Length L Ch R = 1 ,8354.2  ,253.6,250,248.6
XS GIS Cut Line= 3
     2141587.207      225737.394     2141223.159       225782.22
     2140863.319      225834.667
#Sta/Elev= 30
       0 2443.55    55.7 2423.49      72 2421.62   137.6 2407.16   199.8 2397.78
     226 2395.17   235.8 2393.07   248.9 2393.84   265.3 2392.11   278.4 2388.01
  286.392387.305  317.642388.291   350.4 2388.46   360.2 2384.23   366.8 2383.36
   374.3 2384.29   386.4 2387.02     393 2390.48   406.1 2401.16   412.7 2404.86
     429 2416.56   461.8 2437.32     488 2455.66     547 2499.56     606 2545.09
   635.4  2568.6     642 2575.35   648.5 2580.37   691.1 2605.85   730.4 2626.86
#Mann= 5 ,-1 , 0
       0     .12       0  286.39    .016       0  317.64     .12       0
   360.2    .045       0   374.3     .12       0
Bank Sta=360.2,374.3
XS Rating Curve= 0 ,0
Exp/Cntr=0.3,0.1

Type RM Length L Ch R = 1 ,8104.2  ,281,281.7,279.2
XS GIS Cut Line= 3
     2141562.494      225428.428     2141214.817      225533.895
     2140851.924      225604.593
#Sta/Elev= 30
       0 2429.39    58.9 2412.94    78.6 2409.03     108 2401.32   130.9 2396.69
   186.6 2390.26   212.8 2384.08   219.3 2383.14   258.6  2383.9   271.7 2383.21
  286.872384.149   301.1 2383.86     311 2381.37  318.952380.965     347  2381.4
   356.8 2378.87   363.3 2378.13   370.8 2378.84     383 2379.96   389.5 2382.11
   399.3 2390.97   445.1 2426.45   454.9 2433.18   510.6 2467.87   546.5 2491.22
   618.5 2535.37   631.6 2539.21   644.7  2546.6   670.9 2556.17     733 2575.68
#Mann= 5 ,-1 , 0
       0     .12       0  286.87    .016       0  318.95     .12       0
   356.8    .045       0   370.8     .12       0
Bank Sta=356.8,370.8
XS Rating Curve= 0 ,0
Exp/Cntr=0.3,0.1

Type RM Length L Ch R = 1 ,7822.6  ,222.5,218.3,208.9
XS GIS Cut Line= 2
     2141511.592      225163.002     2140820.403       225363.74
#Sta/Elev= 30
       0 2454.84    26.2 2442.99    75.2 2418.33   117.8 2401.25   163.6  2389.6
   183.2 2386.24     229 2381.04   258.5 2380.73   274.8 2376.78  295.532377.283
   320.6 2375.05   327.2  2375.3  331.812373.576     337 2372.46   343.7 2373.52
   359.9 2376.08   395.9 2376.74   405.7 2379.19   490.7 2419.53   507.1 2423.89
   523.4 2426.16   569.3 2448.36   598.7 2464.95   608.5 2467.16   618.3 2473.17
   644.5 2485.83   657.6 2493.27   667.4 2495.43   680.5 2502.57   719.8 2520.71
#Mann= 4 ,-1 , 0
       0     .12       0  295.53    .016       0  331.81    .045       0
   343.7     .12       0
#XS Ineff= 2 , 0
          327.18 2377.86  374.21         2378.38
Permanent Ineff=
       F       F
Bank Sta=331.81,343.7
XS Rating Curve= 0 ,0
Exp/Cntr=0.3,0.1

Type RM Length L Ch R = 1 ,7604.2  ,253.1,250,248.6
XS GIS Cut Line= 3
     2141407.447      224884.786     2141081.948      225073.757
     2140793.293      225300.992
#Sta/Elev= 30
       0 2481.85    94.9 2451.68   124.4 2441.02   186.6 2413.64     216 2398.97
   245.5 2386.21   271.6 2372.79   278.2 2372.02  324.26 2372.83   350.2 2372.97
  366.122368.665   368.9  2368.1   373.1 2367.68  380.762368.132   389.5 2370.75
   399.3 2372.07   425.6 2372.74   435.4 2370.66   461.7 2373.04   484.6 2376.24
   497.7 2380.57   537.1 2398.84   586.3 2425.13   645.3 2454.67   661.7 2464.39
   671.6 2466.26   681.4 2473.39   727.3 2499.65   737.2 2502.72   743.7 2506.93
#Mann= 5 ,-1 , 0
       0     .12       0  324.26    .016       0  366.12     .12       0
   368.9    .045       0  380.76     .12       0
#XS Ineff= 2 , 0
                          422.22          2373.8
Permanent Ineff=
       F       F
Bank Sta=368.9,380.76
XS Rating Curve= 0 ,0
Exp/Cntr=0.3,0.1

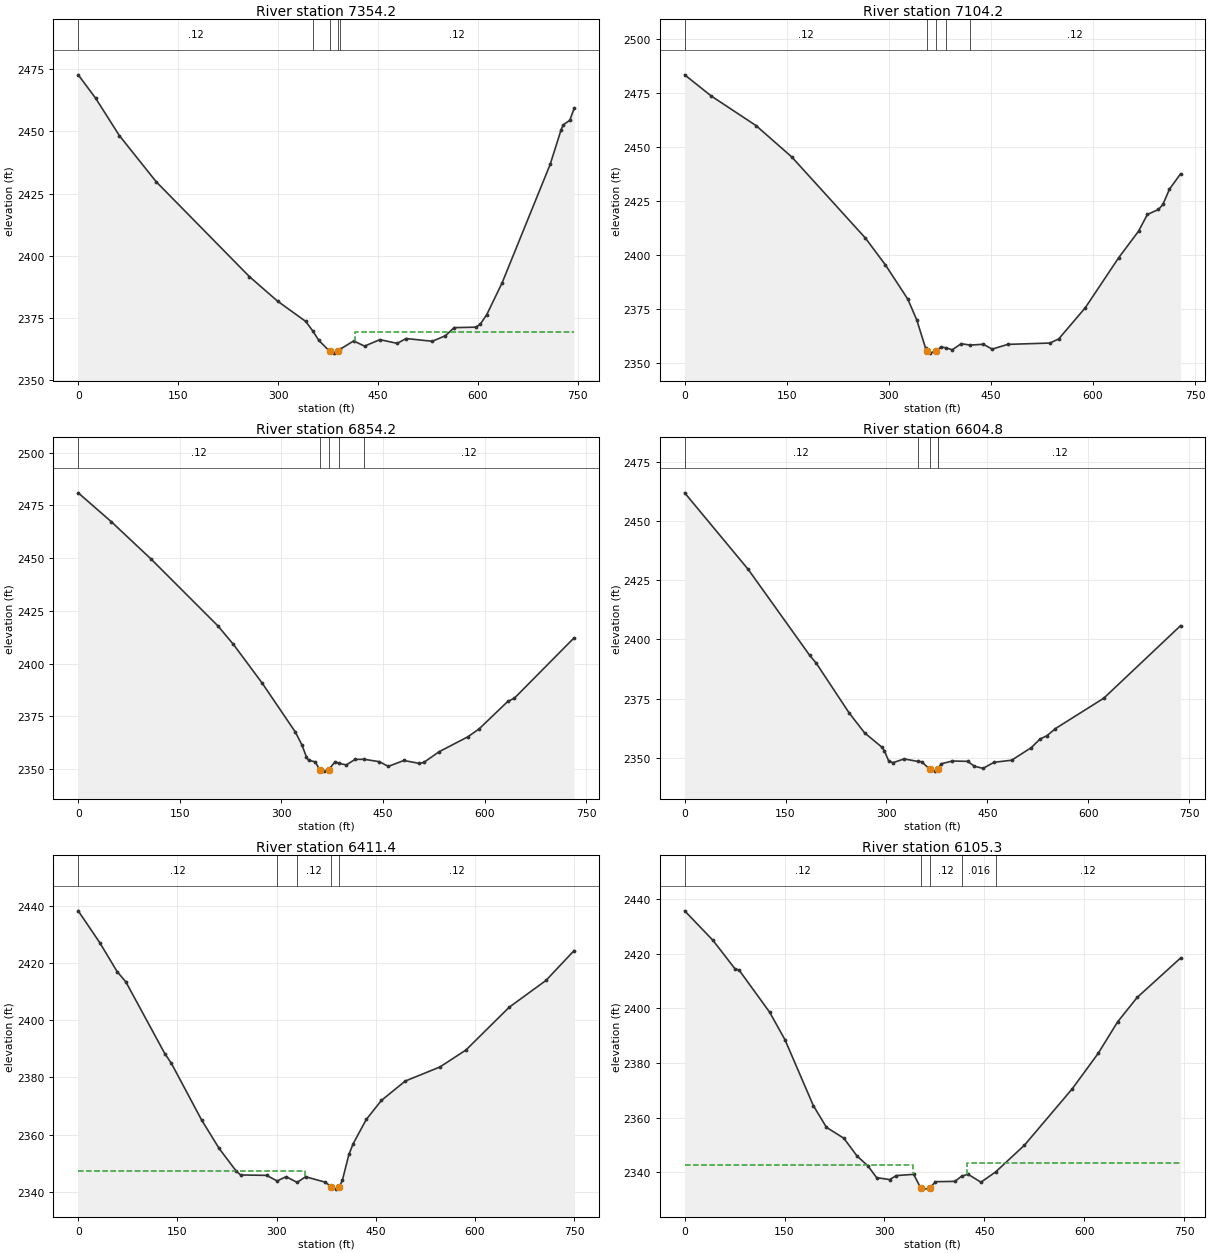
Type RM Length L Ch R = 1 ,7354.2  ,239.1,250,259.3
XS GIS Cut Line= 3
     2141271.058       224660.14     2140962.281      224888.306
     2140669.725      225098.919
#Sta/Elev= 30
       0 2472.65      26 2463.32    61.8 2448.26   117.1 2429.73     257 2391.67
   299.3 2381.82   341.6 2373.68  352.212369.821   361.2 2366.08   377.4 2361.73
   383.9 2360.97   390.5 2361.74  393.692362.629   413.4 2365.85   429.8 2363.79
   452.8 2366.38     479 2364.88   492.1 2366.83   531.4 2365.73   551.1 2367.94
   564.2  2371.2   596.9 2371.39   603.5 2372.59   613.3 2376.45   636.3 2389.18
   708.4  2436.7   724.8 2450.56     728 2452.57   737.9 2454.41   744.4 2459.19
#Mann= 5 ,-1 , 0
       0     .12       0  352.21    .016       0   377.4    .045       0
   390.5    .016       0  393.69     .12       0
#XS Ineff= 2 , 0
                          415.27         2369.53
Permanent Ineff=
       F       F
Bank Sta=377.4,390.5
XS Rating Curve= 0 ,0
Exp/Cntr=0.3,0.1

Type RM Length L Ch R = 1 ,7104.2  ,252,250,246.9
XS GIS Cut Line= 3
     2141245.568      224592.479     2140887.164      224655.728
     2140529.281      224726.422
#Sta/Elev= 30
       0 2483.34    39.4 2473.49   104.9 2459.89   157.4  2445.4   265.6 2407.93
   295.1 2395.49   327.9 2379.71     341 2370.16   354.1 2356.97   356.4 2355.83
   360.7 2354.78   368.72355.805     377 2357.64   384.72357.157   393.3 2356.33
   406.3 2359.14  419.35  2358.5   438.9 2358.86   451.9 2356.63   474.7 2358.82
   536.6 2359.44   549.6 2361.33   588.7 2375.75   637.5 2398.75   666.9  2411.1
   679.9 2418.83   696.2 2421.14   702.7 2423.44   712.4 2430.55   728.7 2437.62
#Mann= 5 ,-1 , 0
       0     .12       0   356.4    .045       0   368.7     .12       0
   384.7    .016       0  419.35     .12       0
Bank Sta=356.4,368.7
XS Rating Curve= 0 ,0
Exp/Cntr=0.3,0.1

Type RM Length L Ch R = 1 ,6854.2  ,244.7,249.4,251.9
XS GIS Cut Line= 3
     2141179.591      224310.581     2140831.238      224413.037
     2140479.508      224524.792
#Sta/Elev= 30
       0    2481    49.1 2467.24     108 2449.47   206.1 2417.96     229  2409.2
   271.5 2390.83   320.6 2367.58   330.4 2361.39   336.9 2355.82   340.2 2354.19
     350 2353.44   356.6 2349.61   363.1 2349.04   369.6 2349.71   379.4  2353.5
  385.592352.702   395.8 2351.98   408.8 2354.61  422.192354.657   444.8 2353.51
   457.8 2351.28   480.7 2354.08   503.6 2352.71   510.1 2353.14   532.9 2358.24
   575.4 2365.34   591.7 2369.01   634.2 2382.08     644 2383.63   732.2 2412.27
#Mann= 5 ,-1 , 0
       0     .12       0   356.6    .045       0   369.6     .12       0
  385.59    .016       0  422.19     .12       0
Bank Sta=356.6,369.6
XS Rating Curve= 0 ,0
Exp/Cntr=0.3,0.1

Type RM Length L Ch R = 1 ,6604.8  ,190,193.5,196.1
XS GIS Cut Line= 3
     2141126.585      224136.151     2140753.812      224178.887
     2140397.417      224243.423
#Sta/Elev= 30
       0 2461.96    94.6 2429.56     186 2393.23   195.8  2389.9   244.7 2368.87
   267.5 2360.52   293.6 2354.37   296.9 2352.95   303.4 2348.57     310 2347.91
   326.3 2349.48  346.852348.413   352.4 2348.29  364.152345.213     372 2344.32
  376.162345.242  377.292345.738   381.7 2347.43   398.1  2348.6   420.9 2348.45
   430.7  2346.4   443.7 2345.49     460 2348.06   486.2 2348.93   515.5 2354.28
   528.6 2357.95   538.4 2359.23   551.4 2362.32   623.2 2375.15   737.4 2405.82
#Mann= 5 ,-1 , 0
       0     .12       0  346.85    .016       0  364.15    .045       0
  376.16    .016       0  377.29     .12       0
Bank Sta=364.15,376.16
XS Rating Curve= 0 ,0
Exp/Cntr=0.3,0.1

Type RM Length L Ch R = 1 ,6411.4  ,299.7,306.1,308
XS GIS Cut Line= 2
     2141086.245      224006.318     2140336.462      224011.743
#Sta/Elev= 30
       0 2438.22    32.7 2427.05    58.9 2416.96      72 2413.39     131 2388.28
   140.8 2384.94   186.6  2365.1   212.8 2355.26     239 2347.21   245.6 2345.89
   284.9 2345.75  300.842343.802   314.3  2345.3  330.982343.297   343.8 2345.26
   373.3 2343.38   382.7 2341.76   389.6 2340.94  395.012341.765   399.5 2344.14
   409.3 2353.07   415.8 2356.86   435.5 2365.28   458.4 2371.94   494.4 2378.71
   546.8 2383.63   586.1 2389.54   651.6 2404.52   707.2 2413.88   749.8 2424.34
#Mann= 5 ,-1 , 0
       0     .12       0  300.84    .016       0  330.98     .12       0
   382.7    .045       0  395.01     .12       0
#XS Ineff= 2 , 0
          343.45 2347.26
Permanent Ineff=
       F       F
Bank Sta=382.7,395.01
XS Rating Curve= 0 ,0
Exp/Cntr=0.3,0.1

Type RM Length L Ch R = 1 ,6105.3  ,260.4,250,239.6
XS GIS Cut Line= 3
     2141120.019      223791.475     2140765.664      223725.855
     2140383.366      223684.629
#Sta/Elev= 30
       0 2435.61    42.6  2424.8    75.4 2414.49    81.9 2413.92   127.8 2398.51
   150.7 2388.49   193.3 2364.43     213  2356.5   239.2  2352.5   258.8 2346.06
   275.2 2342.44   288.3 2338.13     308  2337.4   317.8 2338.87     344 2339.32
  354.922334.158   357.1 2333.92   367.9 2334.18   376.7 2336.64     406 2336.75
  416.022338.658   425.6 2339.36   445.1 2336.45  467.082340.202   510.3 2349.96
     582 2370.53   621.1 2383.52   650.4 2395.07   679.7 2403.96   744.9 2418.38
#Mann= 5 ,-1 , 0
       0     .12       0  354.92    .045       0   367.9     .12       0
  416.02    .016       0  467.08     .12       0
#XS Ineff= 2 , 0
          343.45 2342.91  423.53         2343.31
Permanent Ineff=
       F       F
Bank Sta=354.92,367.9
XS Rating Curve= 0 ,0
Exp/Cntr=0.3,0.1

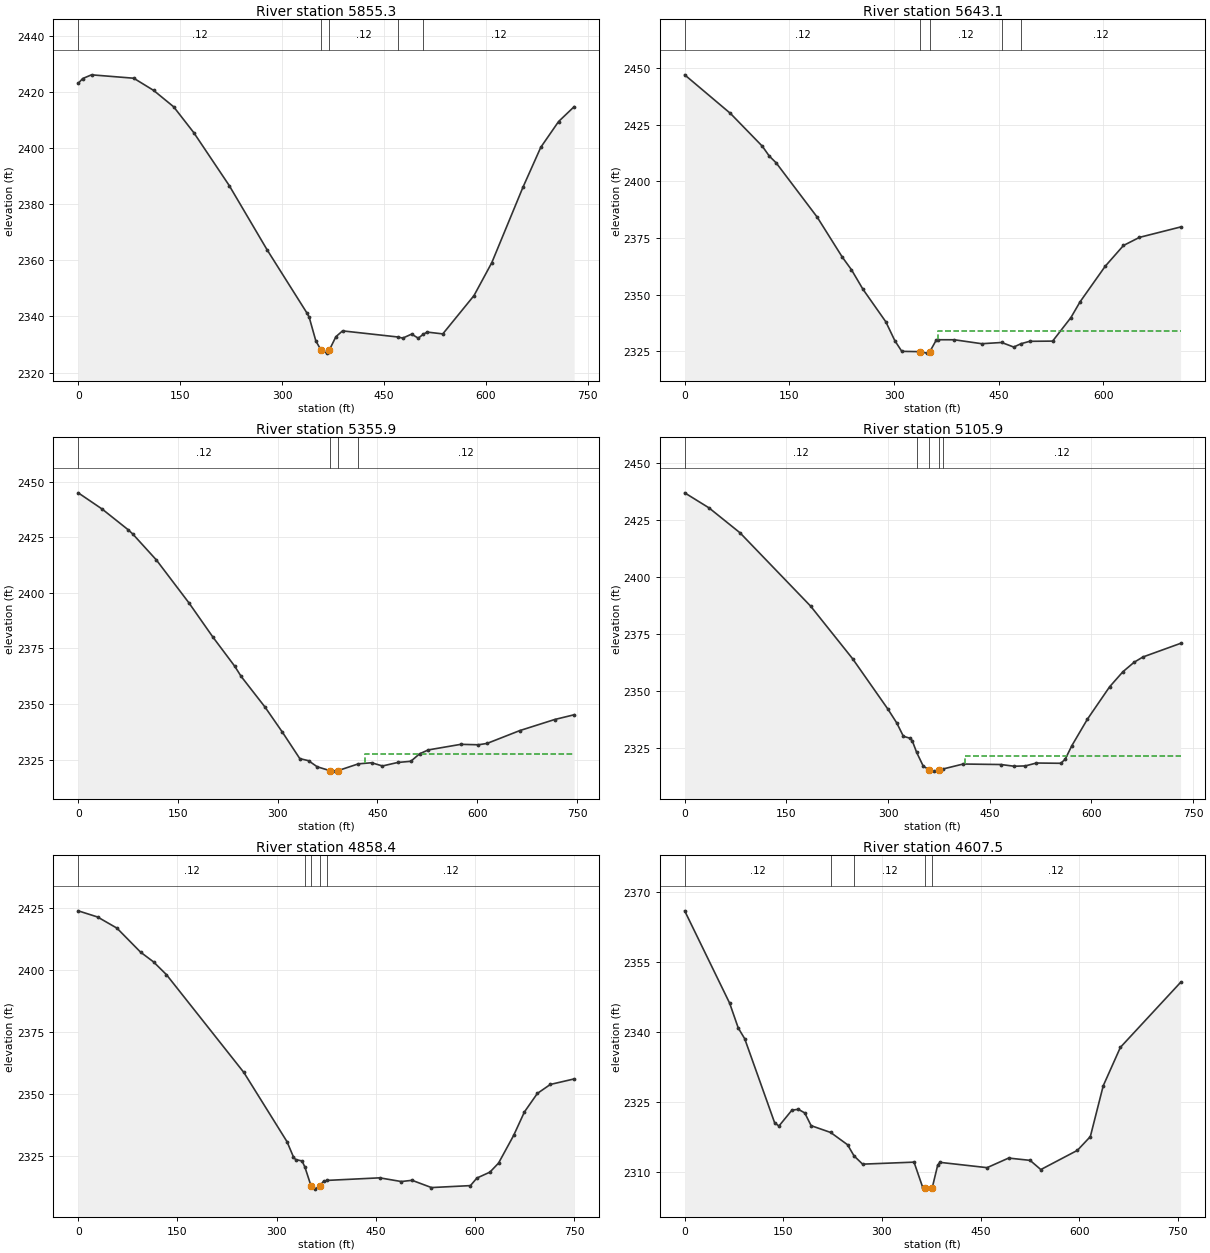
Type RM Length L Ch R = 1 ,5855.3  ,210.7,212.2,214.3
XS GIS Cut Line= 3
      2141063.48      223382.946     2140712.537      223487.053
     2140370.273      223610.267
#Sta/Elev= 30
       0 2423.05     6.5 2424.77    19.6  2426.1    81.7 2424.89   111.1 2420.53
   140.5  2414.7     170 2405.52   222.2 2386.66   277.8 2363.81   336.6 2341.22
   339.9 2339.71   349.7 2331.26  357.542327.929   366.1 2326.93   369.3 2327.92
   379.2 2332.78     389 2334.86  470.222332.686   477.5 2332.28   490.6  2333.7
   500.4 2332.26  507.742333.651   513.5 2334.43   536.5 2333.78   582.4 2347.43
   608.6 2359.16   654.4 2386.01   680.7 2400.28   706.9 2409.46   729.8 2414.75
#Mann= 5 ,-1 , 0
       0     .12       0  357.54    .045       0   369.3     .12       0
  470.22    .016       0  507.74     .12       0
Bank Sta=357.54,369.3
XS Rating Curve= 0 ,0
Exp/Cntr=0.3,0.1

Type RM Length L Ch R = 1 ,5643.1  ,279.2,287.2,287.5
XS GIS Cut Line= 2
     2140988.589      223204.451     2140298.484      223373.722
#Sta/Elev= 30
       0 2446.97    65.5 2429.97   111.3 2415.48   121.2 2411.16     131  2408.2
   189.9 2384.22   225.9 2366.58     239 2361.03   255.4 2352.46   288.2 2338.09
   301.2 2329.73   311.1 2325.06   337.3 2324.93   347.1 2324.28  351.272324.941
   360.2 2329.89   363.5 2330.18   386.4 2330.17   425.7 2328.43   454.22328.972
   471.5 2326.96  481.862328.426   494.4 2329.49   527.2 2329.58   553.4 2339.95
   566.5 2346.89   602.5 2362.56   628.7 2371.73   651.6 2375.31   710.6  2379.9
#Mann= 5 ,-1 , 0
       0     .12       0   337.3    .045       0  351.27     .12       0
   454.2    .016       0  481.86     .12       0
#XS Ineff= 2 , 0
                          362.44         2334.19
Permanent Ineff=
       F       F
Bank Sta=337.3,351.27
XS Rating Curve= 0 ,0
Exp/Cntr=0.3,0.1

Type RM Length L Ch R = 1 ,5355.9  ,245.6,250,257.9
XS GIS Cut Line= 3
     2140993.197      223017.667     2140607.846      223027.434
     2140252.044      223083.617
#Sta/Elev= 30
       0 2444.92    35.9 2437.64    75.1 2428.32    81.7 2426.51   117.6 2414.71
   166.6  2395.4   202.5 2380.07   235.2 2367.02     245 2362.38   280.9 2348.59
   307.1 2337.28   333.2 2325.42   346.3 2324.49   359.3 2321.76     378 2320.06
   385.5  2319.8  390.892320.049  421.222323.069   441.1 2323.57   457.5 2322.12
   480.4 2323.69   500.1 2324.22   513.2 2327.56   526.3 2329.33   575.4 2331.85
   601.6 2331.65   614.7 2332.25   663.8 2338.01   716.2 2342.99   745.7 2345.14
#Mann= 4 ,-1 , 0
       0     .12       0     378    .045       0  390.89    .016       0
  421.22     .12       0
#XS Ineff= 2 , 0
                          430.96         2327.57
Permanent Ineff=
       F       F
Bank Sta=378,390.89
XS Rating Curve= 0 ,0
Exp/Cntr=0.3,0.1

Type RM Length L Ch R = 1 ,5105.9  ,247.4,247.5,245.3
XS GIS Cut Line= 3
     2141019.626      222841.383     2140654.461      222793.918
     2140299.499      222716.755
#Sta/Elev= 30
       0 2437.12    35.8 2430.53    81.5  2419.6   185.8 2387.36   247.7 2364.27
   299.8 2342.13   312.8 2336.08   322.6 2330.22   332.4 2329.36   335.6 2328.31
  342.222323.105   351.9 2317.11   360.7 2315.49   368.2 2314.92   374.8 2315.52
  380.332315.807   410.8 2318.04   466.4 2317.82     486 2317.07   502.4 2317.21
   518.8 2318.48   554.8 2318.36   561.3 2320.19   571.1 2326.12     594 2337.72
   626.8 2351.96   646.4 2358.57   662.8  2362.7   675.9 2365.04   731.5 2371.03
#Mann= 5 ,-1 , 0
       0     .12       0  342.22    .016       0   360.7    .045       0
   374.8    .016       0  380.33     .12       0
#XS Ineff= 2 , 0
                          413.62         2321.76
Permanent Ineff=
       F       F
Bank Sta=360.7,374.8
XS Rating Curve= 0 ,0
Exp/Cntr=0.3,0.1

Type RM Length L Ch R = 1 ,4858.4  ,265.4,250.9,234.9
XS GIS Cut Line= 3
     2141062.544      222596.744     2140661.983      222546.899
     2140320.266      222604.627
#Sta/Elev= 30
       0 2423.81    29.3 2421.32    58.6 2416.82    94.4 2407.11   113.9  2403.2
   133.5 2398.03   250.6 2358.53   315.8 2330.61   325.5 2324.48   328.8 2323.37
   338.6  2322.8  342.932320.322     352 2312.88   358.1 2311.43   365.8 2312.89
   371.1 2314.58  377.052314.961     456 2315.99   488.7  2314.5     505 2314.99
   534.4 2312.06   593.3 2312.85   603.1 2315.91   622.7 2318.28   635.8 2321.92
   658.7 2333.13     675 2342.61   694.6 2350.09   714.2  2353.7   750.2 2355.93
#Mann= 5 ,-1 , 0
       0     .12       0  342.93    .016       0     352    .045       0
   365.8    .016       0  377.05     .12       0
Bank Sta=352,365.8
XS Rating Curve= 0 ,0
Exp/Cntr=0.3,0.1

Type RM Length L Ch R = 1 ,4607.5  ,232.8,243.9,252.5
XS GIS Cut Line= 3
     2140941.823      222148.269      2140616.07      222340.278
        2140298.      222540.952
#Sta/Elev= 30
       0 2365.89    68.4 2346.14    81.5 2340.83    91.3 2338.54   136.9 2320.54
   143.4 2319.89     163 2323.26   172.8 2323.46   182.6 2322.68   192.3 2319.96
  222.022318.502   247.7 2315.88  257.622313.484   270.6 2311.73   348.8 2312.16
   361.8 2306.84   365.1 2306.55   374.9 2306.39  376.292306.577   384.7 2311.48
   387.9 2312.12   459.9 2310.98   492.6 2313.03   525.3 2312.54   541.6 2310.57
   597.2 2314.68   616.9 2317.62   636.5 2328.48   662.6  2336.7   754.2  2350.6
#Mann= 5 ,-1 , 0
       0     .12       0  222.02    .016       0  257.62     .12       0
   365.1    .045       0  376.29     .12       0
Bank Sta=365.1,376.29
XS Rating Curve= 0 ,0
Exp/Cntr=0.3,0.1

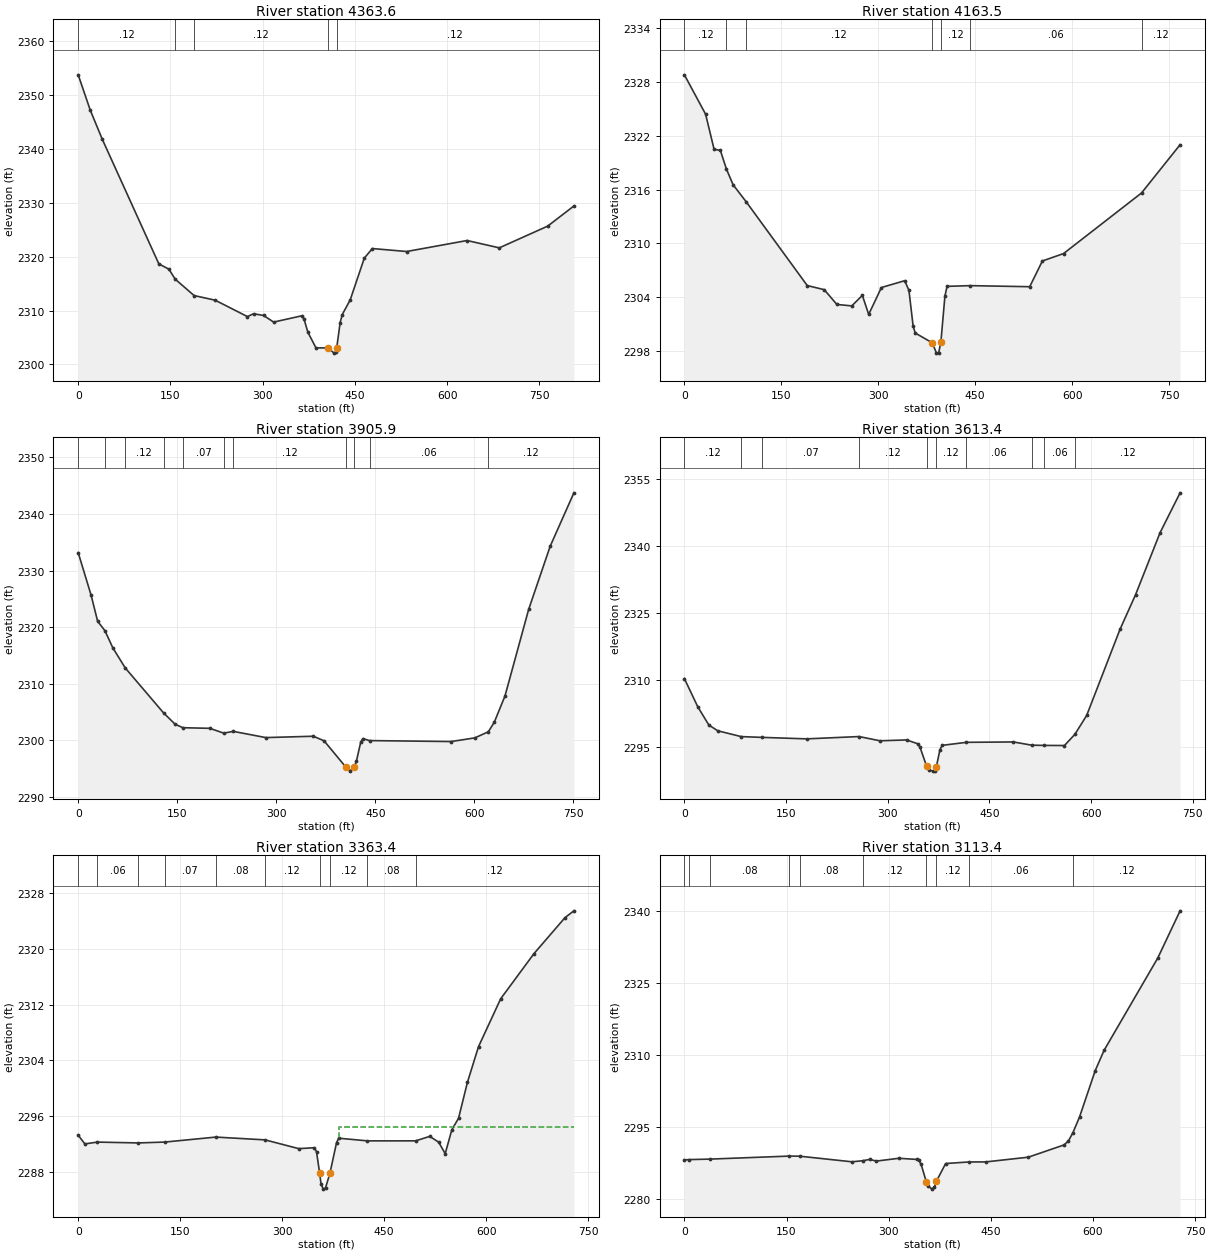
Type RM Length L Ch R = 1 ,4363.6  ,203.4,200,199.5
XS GIS Cut Line= 2
     2140910.464      222118.297     2140112.938      222235.484
#Sta/Elev= 30
       0 2353.74    19.7 2347.15    39.3 2341.74   131.1 2318.66   147.5 2317.67
  157.792315.813  188.442312.777   222.8 2311.91   275.2 2308.87   285.1  2309.4
   301.5 2309.08   317.8 2307.85   363.7 2309.02     367 2308.49   373.6 2305.94
   386.7 2303.06   406.3 2303.06   416.2 2302.09   419.4 2302.21   420.42303.065
     426 2307.76   429.3 2309.22   442.4 2311.99   465.3 2319.73   478.4  2321.5
   534.1 2320.95   632.4 2322.99   684.8 2321.63   763.5 2325.66   806.1  2329.4
#Mann= 5 ,-1 , 0
       0     .12       0  157.79    .016       0  188.44     .12       0
   406.3    .045       0   420.4     .12       0
Bank Sta=406.3,420.4
XS Rating Curve= 0 ,0
Exp/Cntr=0.3,0.1

Type RM Length L Ch R = 1 ,4163.5  ,252,257.7,255.7
XS GIS Cut Line= 2
     2140824.743      221942.516     2140065.194      222049.938
#Sta/Elev= 30
       0 2328.81    32.8 2324.42    45.9 2320.52    55.7 2320.37   65.032318.298
    75.4 2316.54   95.78 2314.63   190.1  2305.3   216.4 2304.84     236 2303.19
     259 2303.03   275.4  2304.2   285.2 2302.08   304.9 2305.08   340.9 2305.84
   347.5 2304.76     354 2300.76   357.3    2300   383.6 2298.91   390.1 2297.76
   393.4 2297.77   396.92298.975   403.2 2304.14   406.5 2305.21  442.39 2305.29
   534.4 2305.17     554 2308.04   586.8 2308.87   707.42315.627   767.1 2321.01
#Mann= 7 ,-1 , 0
       0     .12       0   65.03    .016       0   95.78     .12       0
   383.6    .045       0   396.9     .12       0  442.39     .06       0
   707.4     .12       0
Bank Sta=383.6,396.9
XS Rating Curve= 0 ,0
Exp/Cntr=0.3,0.1

Type RM Length L Ch R = 1 ,3905.9  ,294.1,292.4,288.9
XS GIS Cut Line= 3
     2140807.379      221740.381     2140442.473      221767.735
     2140059.985      221810.641
#Sta/Elev= 30
       0 2333.16    19.6 2325.62    29.4 2321.04   40.542319.354    52.3 2316.36
   71.152312.791   129.22304.838     147  2302.8  158.822302.205   199.3  2302.1
  220.512301.246  234.832301.561   284.2 2300.46   356.1  2300.7   372.4 2299.89
   405.12295.282   411.6 2294.53   418.1 2295.28   421.4  2296.3   427.9 2299.64
   431.2 2300.28  441.262299.931   564.9 2299.76   600.8 2300.41  621.182301.485
   630.1 2303.14   646.4 2307.81   682.3 2323.13   714.9  2334.3   750.8 2343.74
#Mann= 11 ,-1 , 0
       0     .12       0   40.54    .016       0   71.15     .12       0
   129.2     .06       0  158.82     .07       0  220.51     .06       0
  234.83     .12       0   405.1    .045       0   418.1     .12       0
  441.26     .06       0  621.18     .12       0
Bank Sta=405.1,418.1
XS Rating Curve= 0 ,0
Exp/Cntr=0.3,0.1

Type RM Length L Ch R = 1 ,3613.4  ,254.1,250,246.4
XS GIS Cut Line= 3
     2140730.975      221416.563     2140371.726      221492.259
     2140016.846      221573.466
#Sta/Elev= 30
       0 2310.42    19.7 2304.12    36.1 2300.02    49.2 2298.74   83.742297.438
  113.932297.265   180.3 2296.93  257.652297.447   288.5  2296.5   327.8 2296.69
   344.2 2295.83   347.5  2295.1   357.3  2290.8   360.6 2289.97   367.1 2289.71
   370.4 2289.84  371.63 2290.66     377 2294.53   380.3 2295.48  415.982296.156
   485.2 2296.24   512.22295.521  530.952295.464   560.6 2295.44  575.972297.934
   593.4 2302.17   642.6 2321.45   665.6 2329.22   701.7 2343.08   731.2 2351.99
#Mann= 10 ,-1 , 0
       0     .12       0   83.74     .06       0  113.93     .07       0
  257.65     .12       0   357.3    .045       0  371.63     .12       0
  415.98     .06       0   512.2     .08       0  530.95     .06       0
  575.97     .12       0
Bank Sta=357.3,371.63
XS Rating Curve= 0 ,0
Exp/Cntr=0.3,0.1

Type RM Length L Ch R = 1 ,3363.4  ,246,250,251.8
XS GIS Cut Line= 3
     2140627.601       221114.16     2140294.685      221260.742
     2139952.892      221390.009
#Sta/Elev= 30
       0 2293.23     9.8 2291.98    28.32292.241   88.262292.119  127.242292.243
  202.48 2292.96  274.87 2292.56   324.4  2291.3   347.4 2291.43   350.6 2290.85
   355.1 2287.83   357.2 2286.24   360.5 2285.48   363.8 2285.65   370.3 2287.76
   380.1 2292.18   383.3  2292.8  425.372292.416  496.44 2292.42   517.1 2293.06
   530.2 2292.24   539.9 2290.58   549.7 2294.03   559.5 2295.66   572.6 2300.84
   588.9 2305.96   621.5 2312.84   670.4 2319.32   716.1  2324.5   729.2 2325.48
#Mann= 10 ,-1 , 0
       0     .12       0    28.3     .06       0   88.26     .08       0
  127.24     .07       0  202.48     .08       0  274.87     .12       0
   355.1    .045       0   370.3     .12       0  425.37     .08       0
  496.44     .12       0
#XS Ineff= 2 , 0
                           383.9         2294.44
Permanent Ineff=
       F       F
Bank Sta=355.1,370.3
XS Rating Curve= 0 ,0
Exp/Cntr=0.3,0.1

Type RM Length L Ch R = 1 ,3113.4  ,249.4,250,250.5
XS GIS Cut Line= 3
     2140567.648      220932.097     2140216.164      221026.727
      2139864.68      221121.358
#Sta/Elev= 30
       0 2288.13    7.442288.191   38.032288.294  154.13 2288.92  169.27  2288.9
     246 2287.73  261.81 2287.95   272.2 2288.23     282 2287.88   314.8 2288.46
     341 2288.23   344.3 2288.03   347.6 2287.23  355.212283.603   357.4  2282.7
     364 2282.04   367.3 2282.47  370.132283.696   383.7 2287.37  417.482287.693
   442.7 2287.71     505 2288.69   557.5 2291.24     564 2292.06  570.692293.826
   580.4 2297.09   603.4 2306.73   616.5 2310.97   695.2 2330.16     728 2339.99
#Mann= 10 ,-1 , 0
       0     .12       0    7.44     .06       0   38.03     .08       0
  154.13     .06       0  169.27     .08       0  261.81     .12       0
  355.21    .045       0  370.13     .12       0  417.48     .06       0
  570.69     .12       0
Bank Sta=355.21,370.13
XS Rating Curve= 0 ,0
Exp/Cntr=0.3,0.1

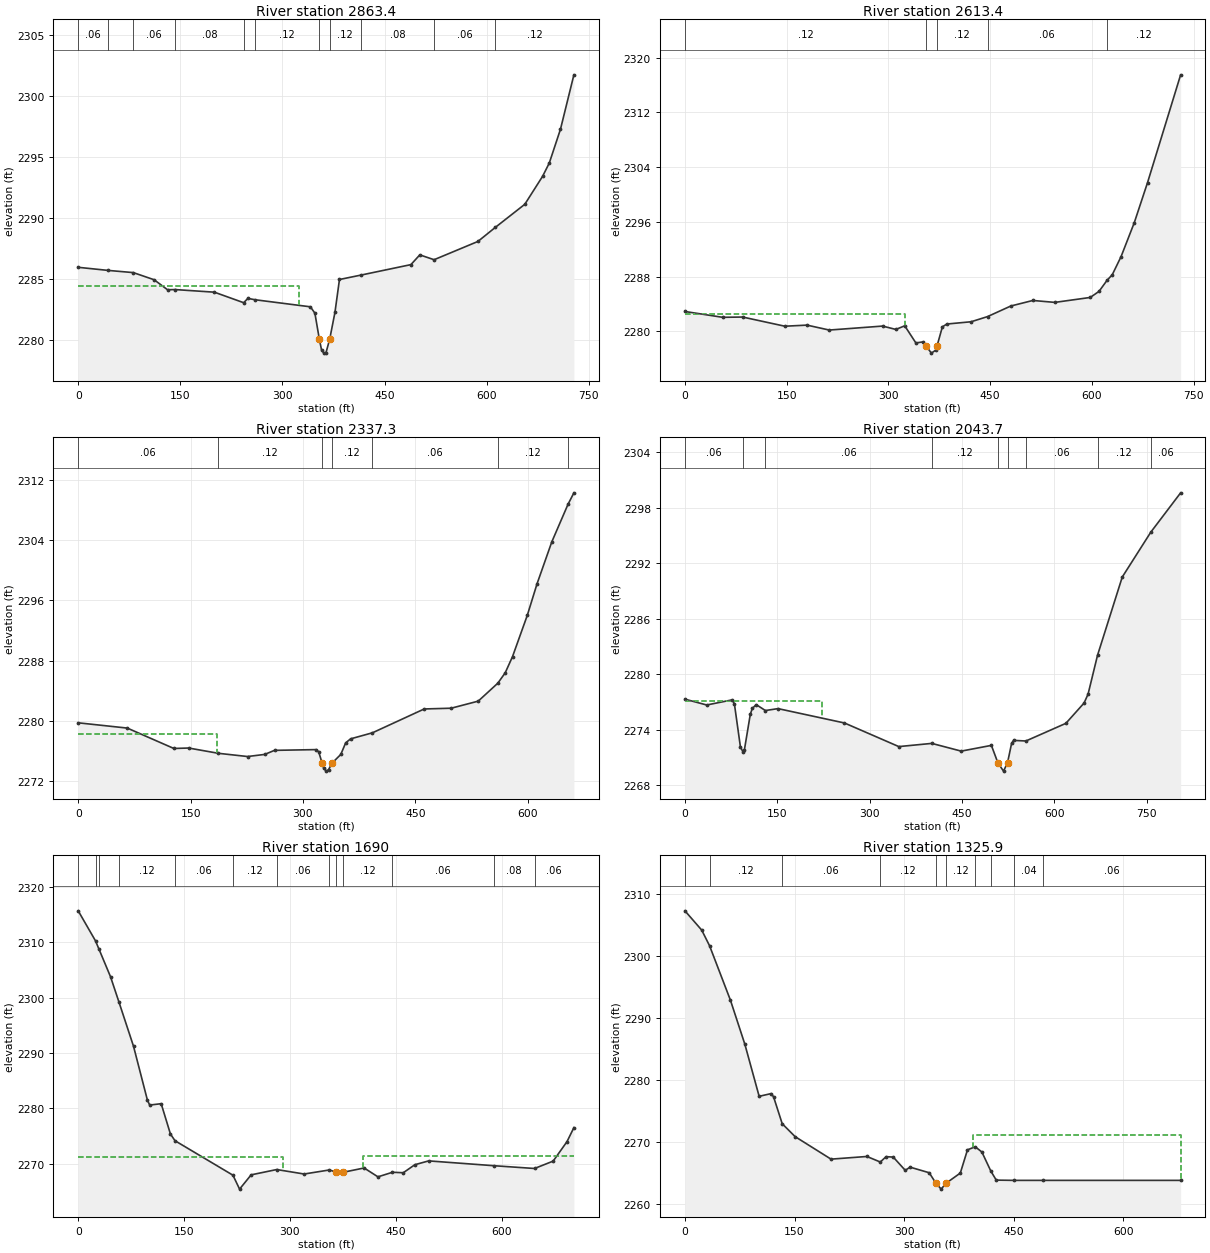
Type RM Length L Ch R = 1 ,2863.4  ,252.9,250,245.7
XS GIS Cut Line= 3
     2140501.322      220701.077     2140147.484      220786.488
     2139793.647      220871.898
#Sta/Elev= 30
       0 2285.98   43.712285.727   80.932285.546   111.5 2284.96   131.2 2284.14
  142.552284.153     200 2283.94  243.012283.076   249.2 2283.43  260.022283.317
     341 2282.74   347.6 2282.22   354.2 2280.07   357.4  2279.2   360.7 2278.94
     364 2278.99  369.432280.102   377.1 2282.29   383.7 2284.98   415.1 2285.34
   488.6  2286.2   501.7    2287  522.672286.603     587  2288.1  612.792289.263
   655.9 2291.15   682.1 2293.45   691.9 2294.54   708.3 2297.31     728 2301.77
#Mann= 11 ,-1 , 0
       0     .06       0   43.71     .08       0   80.93     .06       0
  142.55     .08       0  243.01     .06       0  260.02     .12       0
   354.2    .045       0  369.43     .12       0   415.1     .08       0
  522.67     .06       0  612.79     .12       0
#XS Ineff= 2 , 0
          324.46 2284.48
Permanent Ineff=
       F       F
Bank Sta=354.2,369.43
XS Rating Curve= 0 ,0
Exp/Cntr=0.3,0.1

Type RM Length L Ch R = 1 ,2613.4  ,277.1,276.1,275
XS GIS Cut Line= 3
      2140411.87      220415.319     2140073.654      220548.188
     2139737.877      220697.599
#Sta/Elev= 30
       0 2282.91    55.6 2282.06    85.1  2282.1   147.3 2280.76     180 2280.92
   212.8  2280.2   291.4 2280.78     311 2280.29   324.1 2280.82   340.5 2278.32
   350.3 2278.46   355.9 2277.82   363.4 2276.83   369.9 2277.27   371.62277.833
   379.6 2280.67   386.2 2281.08   421.9 2281.41  446.172282.164   480.5 2283.71
     513 2284.52   545.5 2284.24   597.6 2284.96   610.6 2285.85  622.352287.456
   630.1 2288.28   643.1 2290.93   662.6 2295.89   682.1 2301.73   730.9 2317.47
#Mann= 5 ,-1 , 0
       0     .12       0   355.9    .045       0   371.6     .12       0
  446.17     .06       0  622.35     .12       0
#XS Ineff= 2 , 0
          324.46  2282.5
Permanent Ineff=
       F       F
Bank Sta=355.9,371.6
XS Rating Curve= 0 ,0
Exp/Cntr=0.3,0.1

Type RM Length L Ch R = 1 ,2337.3  ,293,293.7,293.9
XS GIS Cut Line= 2
     2140263.024      220161.483     2139665.802      220446.205
#Sta/Elev= 30
       0 2279.74    65.5 2279.04   127.7 2276.33   147.4 2276.39  187.062275.689
     226 2275.26   248.9 2275.54     262 2276.08   317.7 2276.18     321 2275.88
  325.422274.427   327.5 2273.74   330.8 2273.32   334.1 2273.51  339.032274.406
   350.5 2275.54     357 2277.08   363.6 2277.61  392.712278.413   461.8 2281.58
   497.8 2281.68   533.9 2282.62   560.1 2285.01   569.9 2286.38   579.7 2288.54
   599.4 2294.02   612.5 2298.24   632.1 2303.78  653.772308.781   661.6  2310.3
#Mann= 7 ,-1 , 0
       0     .06       0  187.06     .12       0  325.42    .045       0
  339.03     .12       0  392.71     .06       0   560.1     .12       0
  653.77     .06       0
#XS Ineff= 2 , 0
          184.93 2278.21
Permanent Ineff=
       F       F
Bank Sta=325.42,339.03
XS Rating Curve= 0 ,0
Exp/Cntr=0.3,0.1

Type RM Length L Ch R = 1 ,2043.7  ,363.8,353.6,342.9
XS GIS Cut Line= 3
     2140172.747      219770.858     2140132.816      219916.691
     2139539.066      220190.997
#Sta/Elev= 30
       0 2277.31    35.4 2276.68    77.2 2277.24    80.4 2276.78    90.1 2272.17
   94.282271.606    96.5  2271.8   106.2 2275.68   109.4 2276.31   115.8 2276.72
  130.712276.082   151.2 2276.29   259.1 2274.74   347.4 2272.19  401.012272.534
   448.8  2271.7   497.8 2272.32  508.382270.432   517.5 2269.54     524 2270.44
   530.6 2272.53   533.8 2272.86  553.832272.794   618.8  2274.7   648.3 2276.89
   654.8 2277.84  670.17 2282.04   710.4  2290.5  756.762295.344   805.2 2299.59
#Mann= 9 ,-1 , 0
       0     .06       0   94.28     .12       0  130.71     .06       0
  401.01     .12       0  508.38    .045       0     524     .12       0
  553.83     .06       0  670.17     .12       0  756.76     .06       0
#XS Ineff= 2 , 0
          221.88 2277.06
Permanent Ineff=
       F       F
Bank Sta=508.38,524
XS Rating Curve= 0 ,0
Exp/Cntr=0.3,0.1

Type RM Length L Ch R = 1 ,1690    ,363.9,364.1,359.2
XS GIS Cut Line= 2
     2139865.455       219470.51     2139424.483      220017.385
#Sta/Elev= 30
       0 2315.68   24.522310.256   29.162308.847    45.8 2303.78   57.842299.171
    78.4 2291.22      98 2281.54   101.3  2280.6   117.6 2280.85   130.7 2275.38
  137.212274.159  219.322267.933   228.7 2265.42   245.1    2268  281.382268.957
   320.2 2268.15  355.97 2268.88  365.182268.509   375.8 2268.47   405.2 2269.24
   424.8 2267.64  445.392268.464   460.7 2268.38   477.1 2269.83   496.7 2270.52
  589.052269.649  646.692269.147   673.1 2270.48   692.7 2273.99   702.5 2276.53
#Mann= 13 ,-1 , 0
       0     .06       0   24.52     .12       0   29.16     .06       0
   57.84     .12       0  137.21     .06       0  219.32     .12       0
  281.38     .06       0  355.97     .12       0  365.18    .045       0
   375.8     .12       0  445.39     .06       0  589.05     .08       0
  646.69     .06       0
#XS Ineff= 2 , 0
          289.78 2271.25  403.72         2271.45
Permanent Ineff=
       F       F
Bank Sta=365.18,375.8
XS Rating Curve= 0 ,0
Exp/Cntr=0.3,0.1

Type RM Length L Ch R = 1 ,1325.9  ,149.8,147.3,144.5
XS GIS Cut Line= 2
     2139502.608      219296.899     2139158.858      219881.969
#Sta/Elev= 30
       0 2307.24      23 2304.13    33.8 2301.59    62.3 2292.84      82 2285.76
   101.6 2277.36     118  2277.8   121.3 2277.29  133.172272.945   150.8 2270.87
     200 2267.24   249.1 2267.67  267.452266.778   275.4 2267.64   285.2 2267.57
   301.6 2265.44   308.2 2265.95   334.4 2265.05  343.56 2263.37   350.8 2262.41
   357.3 2263.34     377    2265   386.8 2268.74  397.452269.231   406.5 2268.39
  418.812265.312   426.2 2263.86  450.88 2263.82  490.63 2263.82   678.6 2263.82
#Mann= 10 ,-1 , 0
       0     .06       0    33.8     .12       0  133.17     .06       0
  267.45     .12       0  343.56    .045       0   357.3     .12       0
  397.45     .08       0  418.81     .06       0  450.88     .04       0
  490.63     .06       0
#XS Ineff= 2 , 0
                          394.43         2271.06
Permanent Ineff=
       F       F
Bank Sta=343.56,357.3
XS Rating Curve= 0 ,0
Exp/Cntr=0.3,0.1