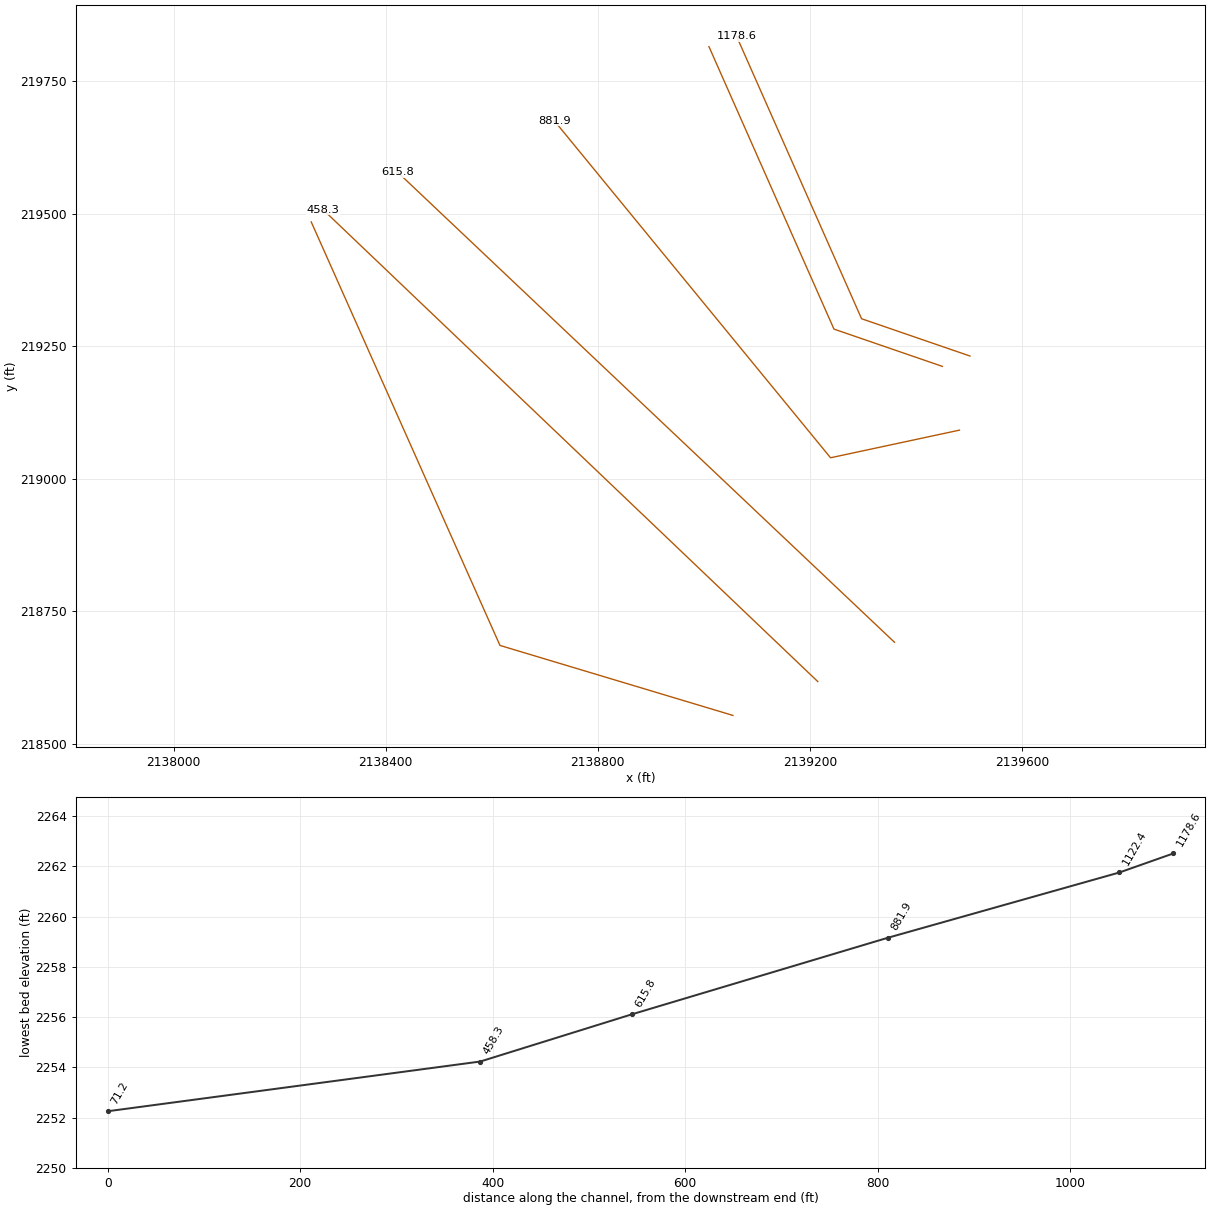
HEC-RAS study FORESTRN.prj: FORESTRN

--- FORESTRN.g01 (geometry) --- (continued)

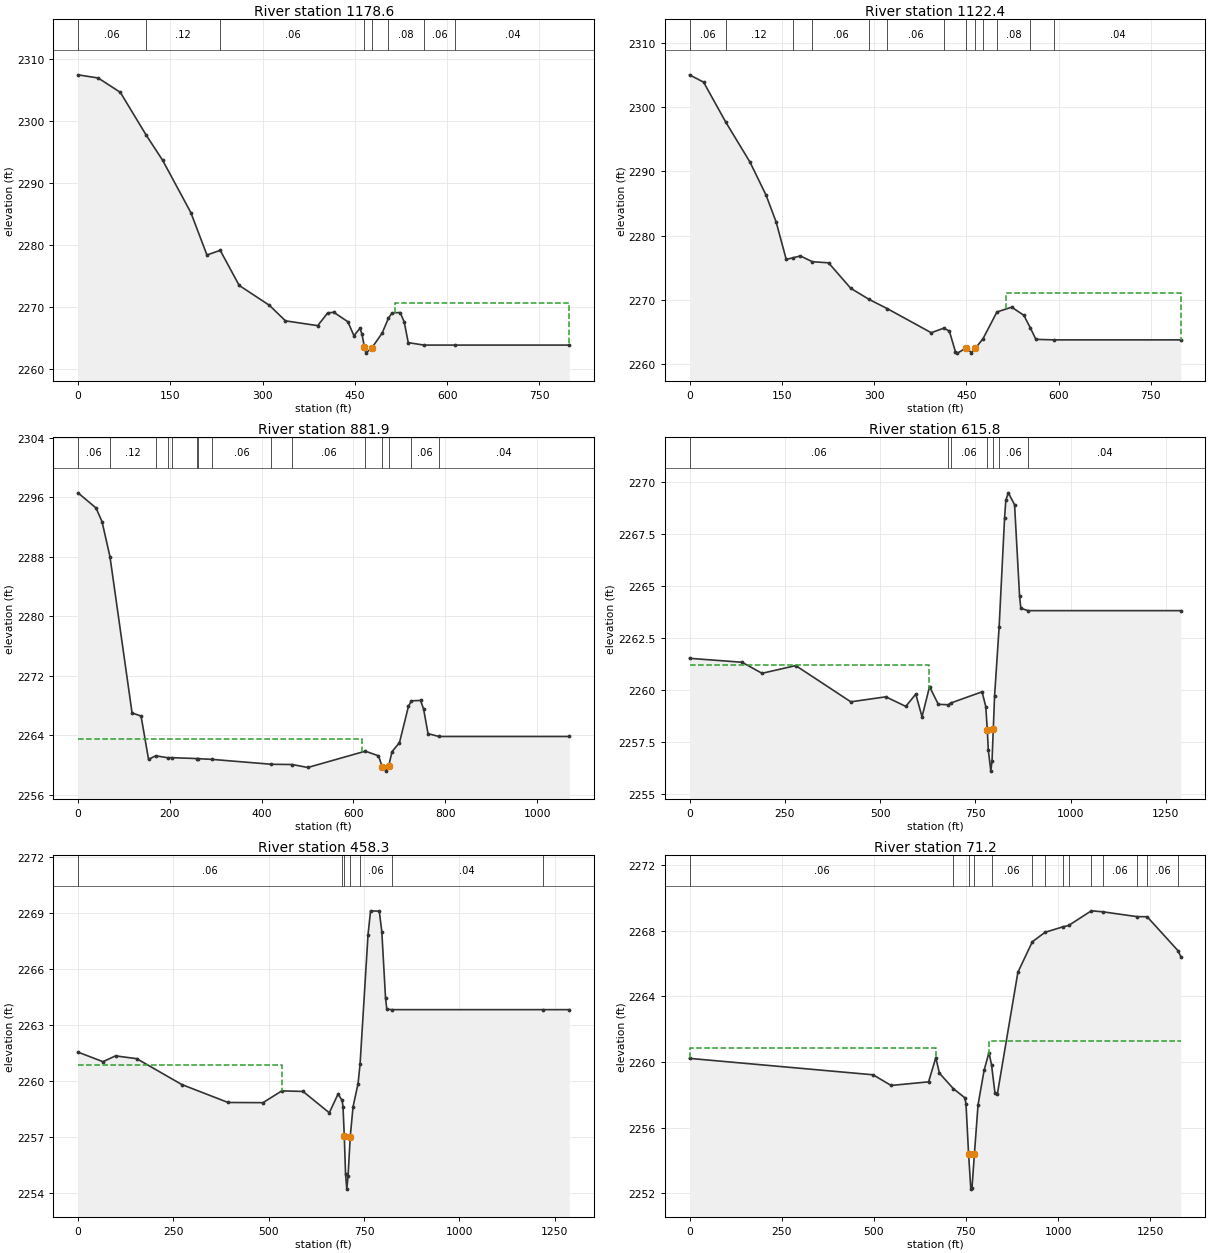
Type RM Length L Ch R = 1 ,1178.6  ,56.5,56.2,56.2
XS GIS Cut Line= 3
     2139501.696      219231.491     2139297.269      219301.804
     2139061.592      219834.356
#Sta/Elev= 30
       0 2307.49    32.8 2306.98    68.8 2304.66  111.172297.699   137.6 2293.68
   183.4 2285.24   209.6 2278.38  231.172279.126     262 2273.46   311.1 2270.25
   337.2 2267.74   389.6 2266.96   405.9 2269.02   415.8 2269.12   438.7 2267.59
   448.5 2265.34   458.3 2266.53   461.6 2265.61  465.652263.441   468.1 2262.52
   477.9 2263.41   494.3 2265.74  504.572268.157   510.6 2269.03   523.7 2269.08
   530.3 2267.54   536.8 2264.22  561.97 2263.82  613.35 2263.82   798.6 2263.82
#Mann= 8 ,-1 , 0
       0     .06       0  111.17     .12       0  231.17     .06       0
  465.65    .045       0   477.9     .06       0  504.57     .08       0
  561.97     .06       0  613.35     .04       0
#XS Ineff= 2 , 0
                          515.17         2270.64
Permanent Ineff=
       F       F
Bank Sta=465.65,477.9
XS Rating Curve= 0 ,0
Exp/Cntr=0.3,0.1

Type RM Length L Ch R = 1 ,1122.4  ,231.8,240.6,245.7
XS GIS Cut Line= 3
     2139449.613       219211.96     2139245.186      219282.273
     2139009.509      219814.825
#Sta/Elev= 30
       0    2305    22.9 2303.86   58.662297.696    98.3 2291.44   124.5 2286.29
   140.8 2282.14   157.2 2276.32  168.282276.573   180.2 2276.86  199.522275.966
     226 2275.79     262 2271.84  291.762270.116  321.672268.663   392.9 2264.93
   413.12265.633   422.3  2265.2   432.1 2262.01   435.4 2261.76  450.042262.572
   458.3 2261.83   464.8 2262.54  477.112264.012  499.672268.155   523.7  2268.9
   543.4 2267.64  554.03 2265.67     563  2263.9  592.41 2263.82   798.6 2263.82
#Mann= 13 ,-1 , 0
       0     .06       0   58.66     .12       0  168.28     .08       0
  199.52     .06       0  291.76     .08       0  321.67     .06       0
   413.1     .12       0  450.04    .045       0   464.8     .12       0
  477.11     .06       0  499.67     .08       0  554.03     .06       0
  592.41     .04       0
#XS Ineff= 2 , 0
                          515.17         2271.15
Permanent Ineff=
       F       F
Bank Sta=450.04,464.8
XS Rating Curve= 0 ,0
Exp/Cntr=0.3,0.1

Type RM Length L Ch R = 1 ,881.9   ,258.7,266.1,253.4
XS GIS Cut Line= 3
     2139481.818      219091.734     2139238.762      219039.651
     2138717.929      219675.068
#Sta/Elev= 30
       0  2296.6    39.2 2294.57    52.3 2292.74   69.652288.014   117.8 2266.99
   137.4 2266.57   153.7 2260.74   169.42261.223  195.662260.958  204.78 2260.97
  260.152260.848  260.432260.843  291.812260.741  421.252260.083  466.762260.047
   500.6 2259.65  625.922261.846   654.5 2261.22  662.612259.778   670.8 2259.16
  676.752259.826   683.9 2261.77   700.3    2263   719.9  2267.9  726.432268.616
   746.1 2268.67   752.7 2267.54   762.5  2264.2  786.25 2263.82  1070.2 2263.82
#Mann= 15 ,-1 , 0
       0     .06       0   69.65     .12       0   169.4     .08       0
  195.66     .06       0  204.78     .08       0  260.15     .12       0
  260.43     .08       0  291.81     .06       0  421.25     .08       0
  466.76     .06       0  625.92     .12       0  662.61    .045       0
  676.75     .12       0  726.43     .06       0  786.25     .04       0
#XS Ineff= 2 , 0
          617.96 2263.51
Permanent Ineff=
       F       F
Bank Sta=662.61,676.75
XS Rating Curve= 0 ,0
Exp/Cntr=0.3,0.1

Type RM Length L Ch R = 1 ,615.8   ,156.6,157.5,156.1
XS GIS Cut Line= 2
     2139359.248      218691.865      2138422.79      219577.845
#Sta/Elev= 30
       0 2261.53   137.8 2261.34   190.3 2260.81   278.8 2261.18   423.2 2259.44
     515 2259.68   567.5 2259.22   593.7 2259.81   610.1 2258.72   629.8 2260.17
   652.8 2259.32  678.91  2259.3  685.732259.384   767.6 2259.92   777.4 2259.21
  781.31 2258.09     784 2257.12   790.6 2256.11   793.8 2256.62   797.1 2258.14
   800.4 2259.71  812.352263.017   826.6 2268.25   829.9 2269.12   836.5 2269.48
   852.9 2268.91     866 2264.53   869.3 2263.93  888.63 2263.82  1289.2 2263.82
#Mann= 7 ,-1 , 0
       0     .06       0  678.91     .12       0  685.73     .06       0
  781.31    .045       0   797.1     .12       0  812.35     .06       0
  888.63     .04       0
#XS Ineff= 2 , 0
          628.48 2261.23
Permanent Ineff=
       F       F
Bank Sta=781.31,797.1
XS Rating Curve= 0 ,0
Exp/Cntr=0.3,0.1

Type RM Length L Ch R = 1 ,458.3   ,334.3,387.1,282.7
XS GIS Cut Line= 2
     2139214.717      218617.646     2138282.425      219506.969
#Sta/Elev= 30
       0 2261.55    65.6 2261.04    98.4 2261.35   154.1  2261.2   272.1 2259.82
   393.4 2258.86   485.2 2258.85   534.4 2259.48   590.1 2259.45     659 2258.31
   681.9 2259.31  692.632258.971     695 2258.63   698.3 2257.06   701.6 2255.05
   704.9 2254.23   708.2 2254.92   713.9 2257.03   721.3 2258.63   734.4 2259.87
  739.642260.893   760.6 2267.83   767.2  2269.1   790.1 2269.08   796.7 2267.99
   806.5 2264.43   809.8 2263.85  822.25 2263.82 1218.17 2263.82  1288.4 2263.82
#Mann= 7 ,-1 , 0
       0     .06       0  692.63     .12       0   698.3    .045       0
   713.9     .12       0  739.64     .06       0  822.25     .04       0
 1218.17     .06       0
#XS Ineff= 2 , 0
          534.57 2260.84
Permanent Ineff=
       F       F
Bank Sta=698.3,713.9
XS Rating Curve= 0 ,0
Exp/Cntr=0.3,0.1

Type RM Length L Ch R = 1 ,71.2    ,87.8,71.2,76.4
XS GIS Cut Line= 3
     2139054.691      218553.844     2138615.455      218685.788
     2138259.552      219484.399
#Sta/Elev= 30
       0 2260.22   497.9 2259.22     547 2258.57   648.6 2258.79   668.2 2260.26
     678 2259.32   715.82258.375   746.8 2257.82   750.1 2257.45  757.062254.419
   763.2 2252.25   766.4 2252.33     773 2254.42   782.8 2257.39   799.2 2259.49
   812.3 2260.57  819.312259.841   828.7 2258.11   835.2 2258.05   890.9 2265.47
  930.082267.329  964.562267.906 1014.332268.248 1028.482268.321 1090.042269.215
 1120.472269.158 1214.122268.861 1241.482268.856 1325.382266.784    1333 2266.42
#Mann= 14 ,-1 , 0
       0     .06       0   715.8     .12       0  757.06    .045       0
     773     .12       0  819.31     .06       0  930.08     .08       0
  964.56     .06       0 1014.33     .08       0 1028.48     .06       0
 1090.04     .08       0 1120.47     .06       0 1214.12     .08       0
 1241.48     .06       0 1325.38     .08       0
#XS Ineff= 2 , 0
          667.49 2260.88  813.42         2261.27
Permanent Ineff=
       F       F
Bank Sta=757.06,773
XS Rating Curve= 0 ,0
Exp/Cntr=0.3,0.1

Chan Stop Cuts=-1
Use User Specified Reach Order=0
Composite Channel Slope=5